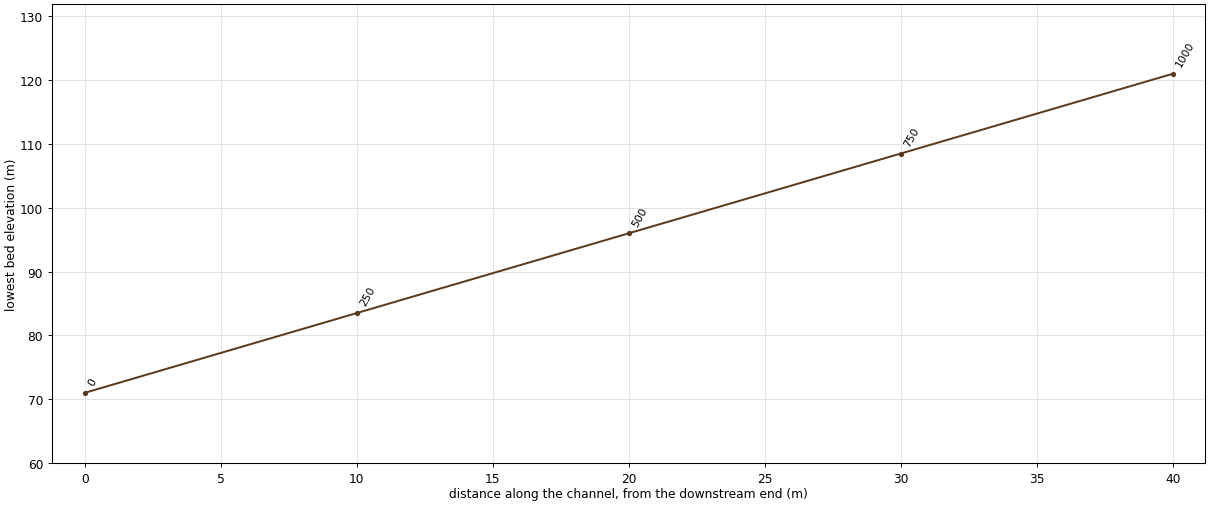
--- EJERCICIO1.prj (project) ---

Proj Title=EJERCICIO1
Current Plan=p01
Default Exp/Contr=0.3,0.1
SI Units
Geom File=g01
Flow File=f02
Plan File=p01
Y Axis Title=Elevation
X Axis Title(PF)=Main Channel Distance
X Axis Title(XS)=Station
BEGIN DESCRIPTION:
END DESCRIPTION:
DSS Export Rating Curves= 0
DSS Export Rating Curve Sorted= 0
DSS Export Volume Flow Curves= 0
DXF OffsetX= 0
DXF OffsetY= 0
DXF ScaleX= 1
DXF ScaleY= 10

--- EJERCICIO1.p01 (plan) ---

Plan Title=PLAN 1
Program Version=5.07
Short Identifier=1
Geom File=g01
Flow File=f02
Supercritical Flow
K Sum by GR= 0
Std Step Tol= 0.01
Critical Tol= 0.01
Num of Std Step Trials= 20
Max Error Tol= 0.3
Flow Tol Ratio= 0.001
Split Flow NTrial= 30
Split Flow Tol= 0.02
Split Flow Ratio= 0.02
Log Output Level= 0
Friction Slope Method= 1
Unsteady Friction Slope Method= 2
Unsteady Bridges Friction Slope Method= 1
Parabolic Critical Depth
Global Vel Dist= 0 , 0 , 0
Global Log Level= 0
CheckData=Verdadero
Encroach Param=-1 ,0,0, 0
Computation Interval=1MIN
Output Interval=1HOUR
Instantaneous Interval=1HOUR
Mapping Interval=1HOUR
Computation Time Step Use Courant=        0
Computation Time Step Use Time Series=    0
Computation Time Step Count To Double=0
Computation Time Step Max Doubling=0
Computation Time Step Max Halving=0
Computation Time Step Residence Courant=0
Run HTab= 0
Run UNet= 0
Run Sediment= 0
Run PostProcess= 0
Run WQNet= 0
Run RASMapper= 0
UNET Theta= 1
UNET Theta Warmup= 1
UNET ZTol= 0.02
UNET ZSATol= 0.02
UNET MxIter= 20
UNET Max Iter WO Improvement= 0
UNET MaxInSteps= 0
UNET DtIC= 0
UNET DtMin= 0
UNET MaxCRTS= 20
UNET WFStab= 2
UNET SFStab= 1
UNET WFX= 1
UNET SFX= 1
UNET 1D Methodology=Finite Difference
UNET DSS MLevel= 4
UNET Pardiso=0
UNET DZMax Abort= 100
UNET Use Existing IB Tables=-1
UNET Froude Reduction=Falso
UNET Froude Limit= 0.8
UNET Froude Power= 4
UNET D1 Cores= 0
UNET D2 Coriolis=0
UNET D2 Cores= 0
UNET D2 Theta= 1
UNET D2 Theta Warmup= 1
UNET D2 Z Tol= 0.01
UNET D2 Volume Tol= 0.01
UNET D2 Max Iterations= 20
UNET D2 Equation= 0
UNET D2 RampUpFraction=0.1
UNET D2 TimeSlices= 1
UNET D2 BCVolumeCheck=0
UNET D1D2 MaxIter= 0
UNET D1D2 ZTol=0.01
UNET D1D2 QTol=0.1
UNET D1D2 MinQTol=1
Write IC File= 0
Write IC File at Fixed DateTime=0
Write IC File at Sim End=0
Echo Input=Falso
Echo Parameters=Falso
Echo Output=Falso
Write Detailed= 0
HDF Write Warmup=0
HDF Write Time Slices=0
HDF Flush=0
HDF Face Node Velocities=0
HDF Compression= 1
HDF Chunk Size= 1
HDF Spatial Parts= 1
HDF Use Max Rows=0
HDF Fixed Rows= 1
Calibration Method= 0
Calibration Iterations= 20
Calibration Max Change=0.05
Calibration Tolerance=0.2
Calibration Maximum=1.5
Calibration Minimum=0.5
Calibration Optimization Method= 1
WQ AD Non Conservative
WQ ULTIMATE=-1
WQ Max Comp Step=1HOUR
WQ Output Interval=15MIN
WQ Output Selected Increments= 0
WQ Output face flow=0
WQ Output face velocity=0
WQ Output face area=0
WQ Output face dispersion=0
WQ Output cell volume=0
WQ Output cell surface area=0
WQ Output cell continuity=0
WQ Output cumulative cell continuity=0
WQ Output face conc=0
WQ Output face dconc_dx=0
WQ Output face courant=0
WQ Output face peclet=0
WQ Output face adv mass=0
WQ Output face disp mass=0
WQ Output cell mass=0
WQ Output cell source sink temp=0
WQ Output nsm pathways=0
WQ Output nsm derived pathways=0
WQ Output MaxMinRange=-1
WQ Daily Max Min Mean=-1
WQ Daily Range=0
WQ Daily Time=0
WQ Create Restart=0
WQ Fixed Restart=0
WQ System Summary=0
WQ Write To DSS=0
WQ Use Fixed Temperature=0
Sorting and Armoring Iterations= 10
XS Update Threshold= 0.02
Bed Roughness Predictor= 0
Hydraulics Update Threshold= 0.02
Energy Slope Method= 1
Volume Change Method= 1
Sediment Retention Method= 0
XS Weighting Method= 0
Number of US Weighted Cross Sections= 1
Number of DS Weighted Cross Sections= 1
Upstream XS Weight=0
Main XS Weight=1
Downstream XS Weight=0
Number of DS XS's Weighted with US Boundary= 1
Upstream Boundary Weight= 1
Weight of XSs Associated with US Boundary= 0
Number of US XS's Weighted with DS Boundary= 1
Downstream Boundary Weight= 0.5
Weight of XSs Associated with DS Boundary= 0.5
Percentile Method= 0
Sediment Output Level= 4
Mass or Volume Output= 0
Output Increment Type= 1
Profile and TS Output Increment= 1
XS Output Flag= 0
XS Output Increment= 10
Write Gradation File= 0
Read Gradation Hotstart= 0
Write HDF5 File= 1
Write Binary Output= 1
Write DSS Sediment File= 0
SV Curve= 0
Specific Gage Flag= 0

--- EJERCICIO1.f02 (steady flow) ---

Flow Title=CAUDAL
Program Version=5.07
Number of Profiles= 1
Profile Names=TR 20 AÑOS
River Rch & RM=CANAL,CANAL           ,1000
     525
Boundary for River Rch & Prof#=CANAL,CANAL           , 1
Up Type= 3
Up Slope=5.027598E-02
Dn Type= 0
DSS Import GetInterval= 0
DSS Import GetPeak= 0
DSS Import FillOption= 0

--- EJERCICIO1.f01 (steady flow) ---

Program Version=5.03
Number of Profiles= 1
Profile Names=TR 20 AÑOS
River Rch & RM=CANAL,CANAL           ,1000
     633
Boundary for River Rch & Prof#=CANAL,CANAL           , 1
Up Type= 3
Up Slope=0.05
Dn Type= 0
DSS Import GetInterval= 0
DSS Import GetPeak= 0
DSS Import FillOption= 0

--- EJERCICIO1.g01 (geometry) ---

Geom Title=GEOMETRIA
Program Version=5.03

River Reach=CANAL           ,CANAL
Reach XY= 3
        0.009375          0.71250.588541666666670.50416666666667
0.588541666666670.50416666666667

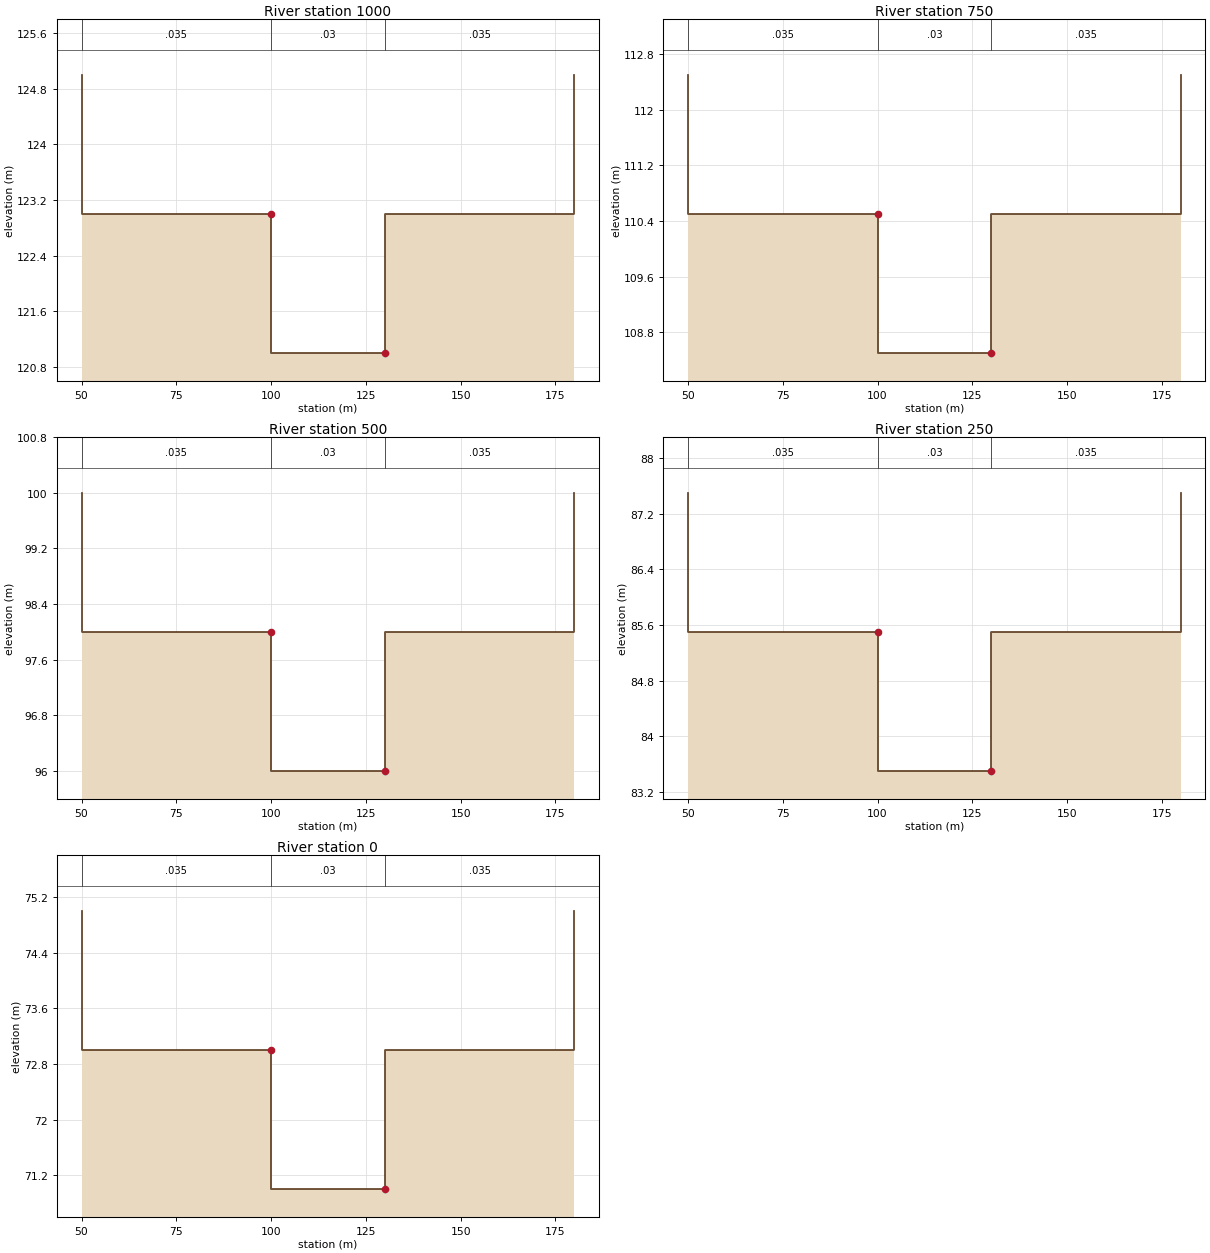
Type RM Length L Ch R = 1 ,1000    ,10,10,10
#Sta/Elev= 8
      50     125      50     123     100     123     100     121     130     121
     130     123     180     123     180     125
#Mann= 3 , 0 , 0
      50    .035       0     100     .03       0     130    .035       0
Bank Sta=100,130
XS Rating Curve= 0 ,0
Exp/Cntr=0.3,0.1

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
Type RM Length L Ch R = 1 ,750     ,10,10,10
#Sta/Elev= 8
      50   112.5      50   110.5     100   110.5     100   108.5     130   108.5
     130   110.5     180   110.5     180   112.5
#Mann= 3 , 0 , 0
      50    .035       0     100     .03       0     130    .035       0
Bank Sta=100,130
XS Rating Curve= 0 ,0
Exp/Cntr=0.3,0.1

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
Type RM Length L Ch R = 1 ,500     ,10,10,10
#Sta/Elev= 8
      50     100      50      98     100      98     100      96     130      96
     130      98     180      98     180     100
#Mann= 3 , 0 , 0
      50    .035       0     100     .03       0     130    .035       0
Bank Sta=100,130
XS Rating Curve= 0 ,0
Exp/Cntr=0.3,0.1

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
Type RM Length L Ch R = 1 ,250     ,10,10,10
#Sta/Elev= 8
      50    87.5      50    85.5     100    85.5     100    83.5     130    83.5
     130    85.5     180    85.5     180    87.5
#Mann= 3 , 0 , 0
      50    .035       0     100     .03       0     130    .035       0
Bank Sta=100,130
XS Rating Curve= 0 ,0
Exp/Cntr=0.3,0.1

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
Type RM Length L Ch R = 1 ,0       ,0,0,0
#Sta/Elev= 8
      50      75      50      73     100      73     100      71     130      71
     130      73     180      73     180      75
#Mann= 3 , 0 , 0
      50    .035       0     100     .03       0     130    .035       0
Bank Sta=100,130
XS Rating Curve= 0 ,0
Exp/Cntr=0.3,0.1
LCMann Table=0

Chan Stop Cuts=-1
Use User Specified Reach Order=0
Composite Channel Slope=5