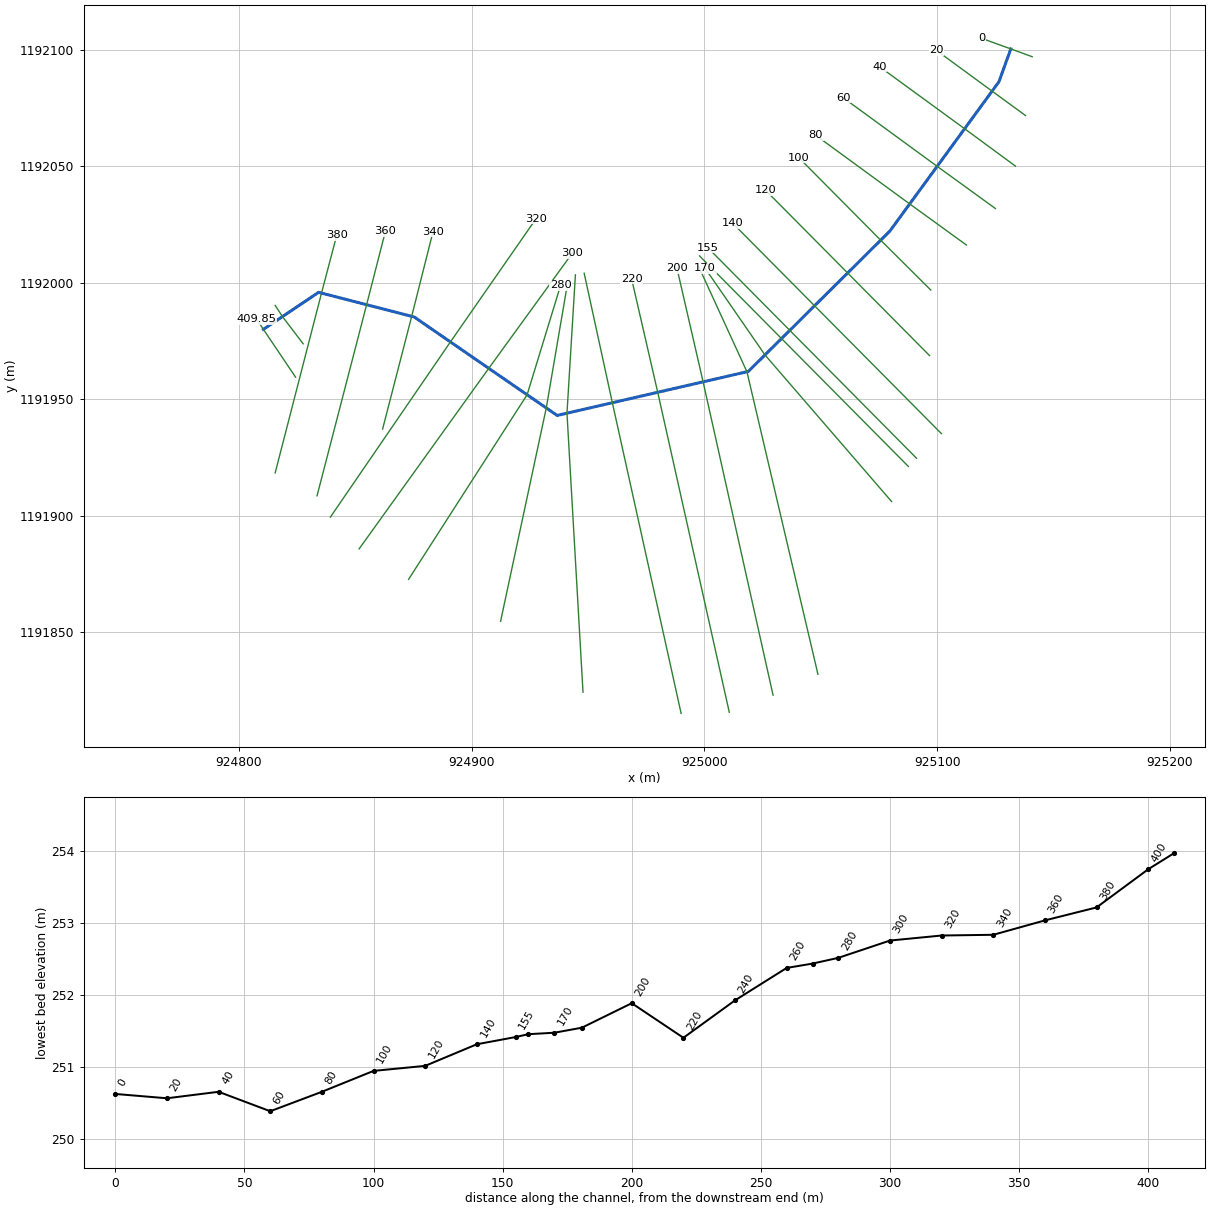
--- PUENTE.prj (project) ---

Proj Title=PUENTE
Current Plan=p01
Default Exp/Contr=0.3,0.1
SI Units
Geom File=g01
Flow File=f01
Plan File=p01
Y Axis Title=Elevation
X Axis Title(PF)=Main Channel Distance
X Axis Title(XS)=Station
BEGIN DESCRIPTION:
END DESCRIPTION:
DSS Export Rating Curves= 0
DSS Export Rating Curve Sorted= 0
DSS Export Volume Flow Curves= 0
DXF OffsetX= 0
DXF OffsetY= 0
DXF ScaleX= 1
DXF ScaleY= 10

--- PUENTE.p01 (plan) ---

Plan Title=Plan 01
Program Version=5.07
Short Identifier=Plan 01
Geom File=g01
Flow File=f01
Subcritical Flow
K Sum by GR= 0
Std Step Tol= 0.003
Critical Tol= 0.003
Num of Std Step Trials= 20
Max Error Tol= 0.1
Flow Tol Ratio= 0.001
Split Flow NTrial= 30
Split Flow Tol= 0.006
Split Flow Ratio= 0.02
Log Output Level= 0
Friction Slope Method= 1
Unsteady Friction Slope Method= 2
Unsteady Bridges Friction Slope Method= 1
Parabolic Critical Depth
Global Vel Dist= 0 , 0 , 0
Global Log Level= 0
CheckData=Falso
Encroach Param=-1 ,0,0, 0
Computation Interval=1MIN
Output Interval=1HOUR
Instantaneous Interval=1HOUR
Mapping Interval=1HOUR
Computation Time Step Use Courant=        0
Computation Time Step Use Time Series=    0
Computation Time Step Count To Double=0
Computation Time Step Max Doubling=0
Computation Time Step Max Halving=0
Computation Time Step Residence Courant=0
Run HTab= 0
Run UNet= 0
Run Sediment= 0
Run PostProcess= 0
Run WQNet= 0
Run RASMapper= 0
UNET Theta= 1
UNET Theta Warmup= 1
UNET ZTol= 0.006
UNET ZSATol= 0.006
UNET MxIter= 20
UNET Max Iter WO Improvement= 0
UNET MaxInSteps= 0
UNET DtIC= 0
UNET DtMin= 0
UNET MaxCRTS= 20
UNET WFStab= 2
UNET SFStab= 1
UNET WFX= 1
UNET SFX= 1
UNET 1D Methodology=Finite Difference
UNET DSS MLevel= 4
UNET Pardiso=0
UNET DZMax Abort= 30
UNET Use Existing IB Tables=-1
UNET Froude Reduction=Falso
UNET Froude Limit= 0.8
UNET Froude Power= 4
UNET D1 Cores= 0
UNET D2 Coriolis=0
UNET D2 Cores= 0
UNET D2 Theta= 1
UNET D2 Theta Warmup= 1
UNET D2 Z Tol= 0.003
UNET D2 Volume Tol= 0.003
UNET D2 Max Iterations= 20
UNET D2 Equation= 0
UNET D2 RampUpFraction=0.1
UNET D2 TimeSlices= 1
UNET D2 BCVolumeCheck=0
UNET D1D2 MaxIter= 0
UNET D1D2 ZTol=0.003
UNET D1D2 QTol=0.1
UNET D1D2 MinQTol=0.03
Write IC File= 0
Write IC File at Fixed DateTime=0
Write IC File at Sim End=0
Echo Input=Falso
Echo Parameters=Falso
Echo Output=Falso
Write Detailed= 0
HDF Write Warmup=0
HDF Write Time Slices=0
HDF Flush=0
HDF Face Node Velocities=0
HDF Compression= 1
HDF Chunk Size= 1
HDF Spatial Parts= 1
HDF Use Max Rows=0
HDF Fixed Rows= 1
Calibration Method= 0
Calibration Iterations= 20
Calibration Max Change=0.05
Calibration Tolerance=0.2
Calibration Maximum=1.5
Calibration Minimum=0.5
Calibration Optimization Method= 1
WQ AD Non Conservative
WQ ULTIMATE=-1
WQ Max Comp Step=1HOUR
WQ Output Interval=15MIN
WQ Output Selected Increments= 0
WQ Output face flow=0
WQ Output face velocity=0
WQ Output face area=0
WQ Output face dispersion=0
WQ Output cell volume=0
WQ Output cell surface area=0
WQ Output cell continuity=0
WQ Output cumulative cell continuity=0
WQ Output face conc=0
WQ Output face dconc_dx=0
WQ Output face courant=0
WQ Output face peclet=0
WQ Output face adv mass=0
WQ Output face disp mass=0
WQ Output cell mass=0
WQ Output cell source sink temp=0
WQ Output nsm pathways=0
WQ Output nsm derived pathways=0
WQ Output MaxMinRange=-1
WQ Daily Max Min Mean=-1
WQ Daily Range=0
WQ Daily Time=0
WQ Create Restart=0
WQ Fixed Restart=0
WQ System Summary=0
WQ Write To DSS=0
WQ Use Fixed Temperature=0
Sorting and Armoring Iterations= 10
XS Update Threshold= 0.02
Bed Roughness Predictor= 0
Hydraulics Update Threshold= 0.02
Energy Slope Method= 1
Volume Change Method= 1
Sediment Retention Method= 0
XS Weighting Method= 0
Number of US Weighted Cross Sections= 1
Number of DS Weighted Cross Sections= 1
Upstream XS Weight=0
Main XS Weight=1
Downstream XS Weight=0
Number of DS XS's Weighted with US Boundary= 1
Upstream Boundary Weight= 1
Weight of XSs Associated with US Boundary= 0
Number of US XS's Weighted with DS Boundary= 1
Downstream Boundary Weight= 0.5
Weight of XSs Associated with DS Boundary= 0.5
Percentile Method= 0
Sediment Output Level= 3
Mass or Volume Output= 0
Output Increment Type= 1
Profile and TS Output Increment= 1
XS Output Flag= 0
XS Output Increment= 10
Write Gradation File= 0
Read Gradation Hotstart= 0
Write HDF5 File= 1
Write Binary Output= 1
Write DSS Sediment File= 0
SV Curve= 0
Specific Gage Flag= 0

--- PUENTE.f01 (steady flow) ---

Flow Title=CAUDAL
Program Version=5.07
Number of Profiles= 1
Profile Names=100 A
River Rch & RM=RIO PUNA PUNA,EJE RIO         ,409.85
  105.16
Boundary for River Rch & Prof#=RIO PUNA PUNA,EJE RIO         , 1
Up Type= 0
Dn Type= 3
Dn Slope=8.090765E-03
DSS Import GetInterval= 0
DSS Import GetPeak= 0
DSS Import FillOption= 0

--- PUENTE.g01 (geometry) ---

Geom Title=GEOMETRIA
Program Version=5.07

River Reach=RIO PUNA PUNA   ,EJE RIO
Reach XY= 9
       925131.64      1192100.46       925126.54      1192086.34
       925079.66      1192022.16       925038.89      1191981.73
       925018.89      1191961.91       924936.77      1191943.01
       924875.38       1191985.3       924834.32      1191995.89
       924810.59      1191979.99

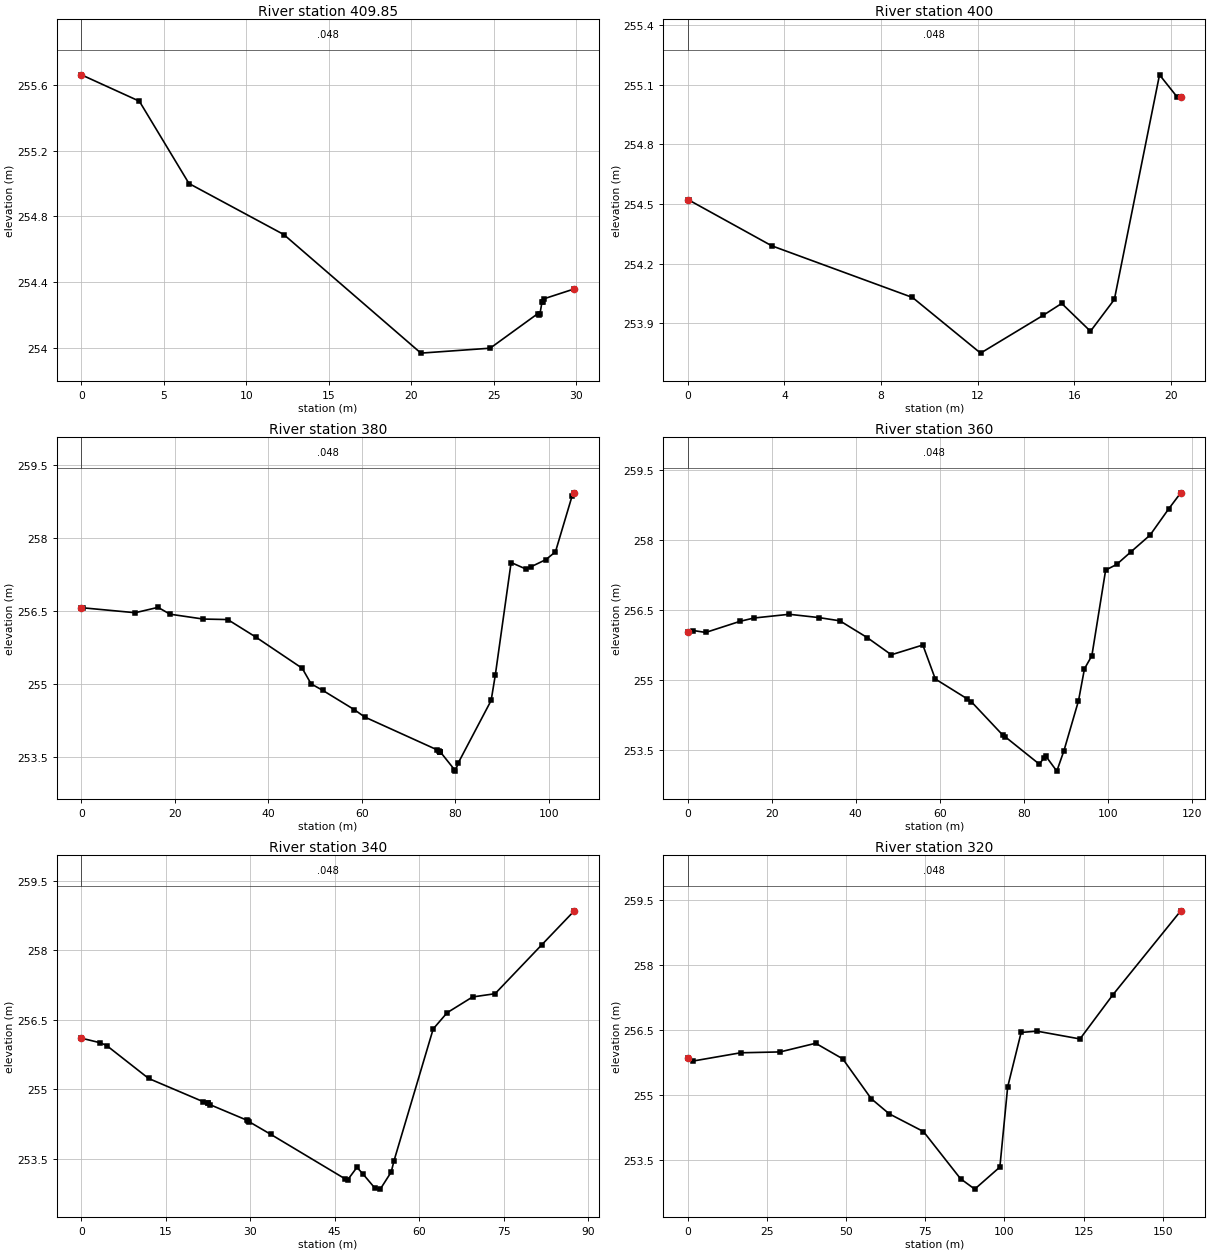
Type RM Length L Ch R = 1 ,409.85  ,9.85,9.85,9.85
XS GIS Cut Line= 3
924824.4232305181191959.44240492924810.5872573531191979.99482353
 924807.748885251191984.23199756
#Sta/Elev= 13
       0  255.66    3.51   255.5    6.52     255   12.27  254.69   20.58  253.97
   24.78     254   27.67  254.21   27.74   254.2    27.8  254.21   27.92  254.28
      28  254.28   28.04   254.3   29.88  254.36
#Mann= 3 , 0 , 0
       0               0       0    .048       0   29.88               0
Bank Sta=0,29.88
XS Rating Curve= 0 ,0
Exp/Cntr=0.3,0.1

Type RM Length L Ch R = 1 ,400     ,20,20,20
XS GIS Cut Line= 3
924827.6861182931191973.77506778924818.7710464311191985.47692986
924815.6709810311191990.25790376
#Sta/Elev= 12
       0  254.52     .04  254.52    3.47  254.29     9.3  254.03   12.12  253.75
   14.71  253.94   15.48     254   16.67  253.86   17.66  254.02   19.53  255.15
   20.25  255.04   20.41  255.04
#Mann= 3 , 0 , 0
       0               0       0    .048       0   20.41               0
Bank Sta=0,20.41
XS Rating Curve= 0 ,0
Exp/Cntr=0.3,0.1

Type RM Length L Ch R = 1 ,380     ,20,20,20
XS GIS Cut Line= 3
924815.6430453481191918.30448277924835.5638004441191995.57306218
924842.087894074 1192020.3618202
#Sta/Elev= 30
       0  256.57     .38  256.57   11.51  256.47   16.38  256.58   18.95  256.44
   26.07  256.34   31.29  256.33   37.31  255.97   47.23  255.33   49.13  255.01
   51.57  254.88   58.39  254.48    60.6  254.33   76.01  253.66   76.53  253.63
   76.64  253.62   76.68  253.61   76.72  253.62    79.8  253.25      80  253.22
   80.56  253.38   87.64  254.67   88.53  255.19   91.91   257.5      95  257.37
   96.11  257.41   99.35  257.56   101.4  257.72  104.97  258.87  105.43  258.93
#Mann= 3 , 0 , 0
       0               0       0    .048       0  105.43               0
Bank Sta=0,105.43
XS Rating Curve= 0 ,0
Exp/Cntr=0.3,0.1

Type RM Length L Ch R = 1 ,360     ,20,20,20
XS GIS Cut Line= 3
924833.6401435321191908.49310501924854.9294265681191990.57581045
924863.0266196791192022.17461369
#Sta/Elev= 30
       0  256.04    1.33  256.06    4.25  256.02   12.46  256.26   15.73  256.33
   24.13  256.41   31.15  256.34    36.2  256.27   42.71  255.91   48.46  255.54
   55.97  255.75   58.94  255.02    66.6  254.59   67.54  254.53   74.95  253.82
   75.56  253.78   83.72  253.19    84.8  253.32    85.2  253.37   87.89  253.04
   89.59  253.48   93.05  254.55   94.48  255.24   96.24  255.52   99.52  257.36
  102.13  257.48  105.52  257.75  110.09  258.11   114.5  258.67  117.42  259.02
#Mann= 3 , 0 , 0
       0               0       0    .048       0  117.42               0
Bank Sta=0,117.42
XS Rating Curve= 0 ,0
Exp/Cntr=0.3,0.1

Type RM Length L Ch R = 1 ,340     ,20,20,20
XS GIS Cut Line= 3
924861.8019233641191937.16449341 924874.295052691191985.57855872
924883.4708836941192022.00990476
#Sta/Elev= 26
       0   256.1    3.36     256    4.49  255.94   11.94  255.23    21.6  254.73
    22.4  254.69   22.43  254.69   22.92  254.66   29.37  254.33   29.57  254.32
   29.73   254.3   33.68  254.02   46.87  253.06    47.3  253.04   48.95  253.31
      50  253.17   52.15  252.86    53.1  252.84   55.04  253.21   55.53  253.45
    62.5   256.3   64.98  256.65   69.49  256.99   73.49  257.06   81.82  258.12
   87.57  258.85
#Mann= 3 , 0 , 0
       0               0       0    .048       0   87.57               0
Bank Sta=0,87.57
XS Rating Curve= 0 ,0
Exp/Cntr=0.3,0.1

Type RM Length L Ch R = 1 ,320     ,20,20,20
XS GIS Cut Line= 3
924839.3669585491191899.34205581924890.9280352011191974.58888579
924927.7312486641192027.55178811
#Sta/Elev= 18
       0  255.85    1.67  255.79   16.63  255.98   29.14     256   40.36   256.2
   48.92  255.84   57.91  254.92   63.59  254.57   74.42  254.16   86.13  253.07
   90.62  252.83   98.56  253.34  101.02  255.19  105.28  256.45  110.27  256.48
  123.87   256.3  134.26  257.32  155.71  259.26
#Mann= 3 , 0 , 0
       0               0       0    .048       0  155.71               0
Bank Sta=0,155.71
XS Rating Curve= 0 ,0
Exp/Cntr=0.3,0.1

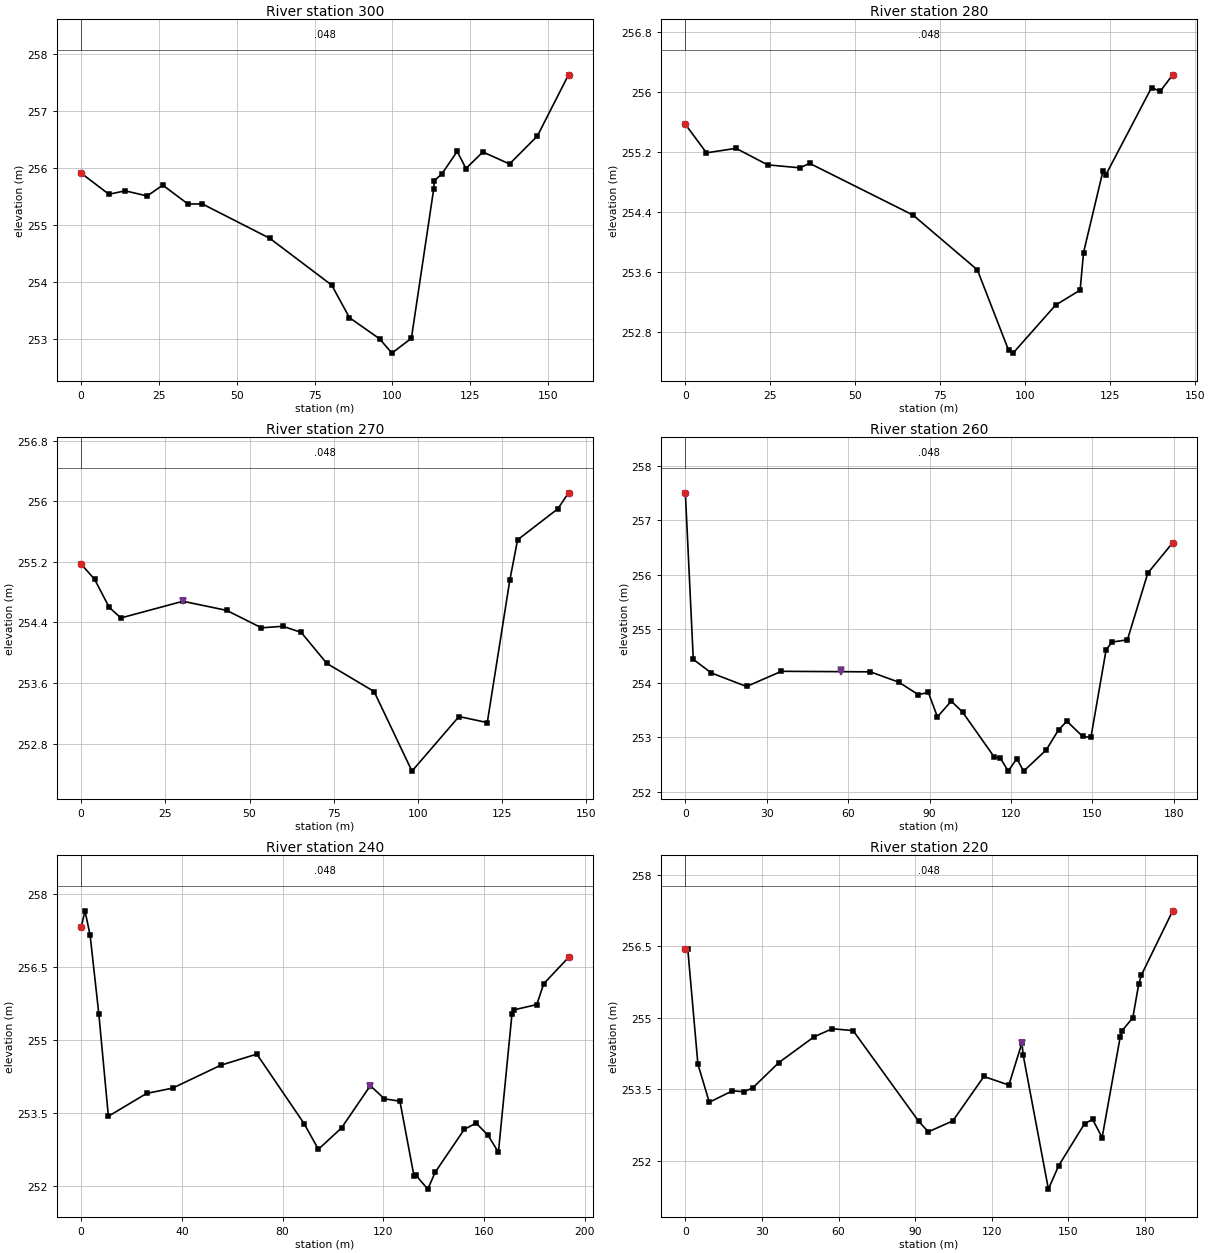
Type RM Length L Ch R = 1 ,300     ,20,20,20
XS GIS Cut Line= 3
 924851.712668061191885.69460201924907.3990501811191963.24403385
  924943.30911671192012.73793631
#Sta/Elev= 22
       0  255.91    8.91  255.54   14.15   255.6   21.21  255.51   26.23   255.7
    34.3  255.37   38.97  255.37   60.59  254.77   80.52  253.95   86.23  253.38
   95.92  253.01   99.85  252.76  106.13  253.02  113.29  255.63  113.49  255.78
  115.84  255.89  120.85  256.29  123.66  255.99  129.09  256.28  137.67  256.07
  146.62  256.56  156.62  257.63
#Mann= 3 , 0 , 0
       0               0       0    .048       0  156.62               0
Bank Sta=0,156.62
XS Rating Curve= 0 ,0
Exp/Cntr=0.3,0.1

Type RM Length L Ch R = 1 ,280     ,10,10,10
XS GIS Cut Line= 3
924872.9754475881191872.63034722 924923.870065161191951.89918191
924938.2760378111191998.94965887
#Sta/Elev= 18
       0  255.57    6.22  255.19   14.92  255.25    24.2  255.03   33.74  254.99
   36.57  255.05   67.01  254.36   85.93  253.63    95.1  252.56   96.43  252.52
  108.94  253.16  116.17  253.36  117.17  253.86   122.9  254.95  123.66  254.89
  137.19  256.06  139.72  256.01  143.41  256.23
#Mann= 3 , 0 , 0
       0               0       0    .048       0  143.41               0
Bank Sta=0,143.41
XS Rating Curve= 0 ,0
Exp/Cntr=0.3,0.1

Type RM Length L Ch R = 1 ,270     ,10,10,10
XS GIS Cut Line= 3
924912.482090499 1191854.6039248 924932.105572651191946.22675594
924940.6831624971191996.49494839
#Sta/Elev= 18
       0  255.17    3.98  254.97    8.33   254.6   11.78  254.46   30.21  254.68
   43.19  254.56   53.54  254.33   59.87  254.35   65.32  254.27   72.95  253.86
   86.97  253.49   98.22  252.44  112.18  253.16  120.58  253.08  127.28  254.96
  129.58  255.49  141.55   255.9   144.7  256.11
#Mann= 3 , 0 , 0
       0               0       0    .048       0   144.7               0
Levee=-1,30.21,254.68,0,,,,
Bank Sta=0,144.7
XS Rating Curve= 0 ,0
Exp/Cntr=0.3,0.1

Type RM Length L Ch R = 1 ,260     ,20,20,20
XS GIS Cut Line= 3
924947.8831191981191824.15715502924940.9953468111191943.98410644
924944.6137130961192003.40127856
#Sta/Elev= 27
       0  257.51    2.92  254.44    9.57  254.19   22.55  253.94   35.39  254.22
   68.16  254.21   78.62  254.02   85.82  253.79   89.53  253.83   92.86  253.38
   97.97  253.67  102.11  253.47   113.8  252.64  116.05  252.62  118.94  252.38
  122.12  252.61  124.63  252.38  132.96  252.77  137.48  253.14  140.57   253.3
  146.35  253.02  149.41     253  155.03  254.62  157.26  254.76  162.86   254.8
  170.38  256.03  179.55  256.59
#Mann= 3 , 0 , 0
       0               0       0    .048       0  179.55               0
Levee=-1,57.44,254.24,0,,,,
Bank Sta=0,179.55
XS Rating Curve= 0 ,0
Exp/Cntr=0.3,0.1

Type RM Length L Ch R = 1 ,240     ,20,20,20
XS GIS Cut Line= 3
924990.0231658281191815.03546481 924960.486032371191948.46887805
924948.3831679241192004.08599001
#Sta/Elev= 28
       0  257.32    1.51  257.66    3.55  257.16    7.03  255.53   10.81  253.43
   25.99   253.9   36.35  254.01   55.39  254.48   69.77  254.71   88.54  253.28
   94.23  252.75  103.42  253.19  114.86  254.06  120.43  253.79  126.62  253.74
  132.24  252.19   132.9  252.22  137.68  251.93  140.65  252.28  152.18  253.16
  156.89  253.29  161.58  253.04  165.74  252.69  171.13  255.54  171.82  255.62
  180.99  255.73  183.75  256.16  193.58   256.7
#Mann= 3 , 0 , 0
       0               0       0    .048       0  193.58               0
Levee=-1,114.86,254.06,0,,,,
Bank Sta=0,193.58
XS Rating Curve= 0 ,0
Exp/Cntr=0.3,0.1

Type RM Length L Ch R = 1 ,220     ,20,20,20
XS GIS Cut Line= 3
925010.7169886111191815.51068243924979.9767179291191952.95364967
924968.7647888961192001.68036357
#Sta/Elev= 29
       0  256.43     .96  256.43    4.91  254.03    9.37  253.23   18.46  253.47
   22.88  253.45   26.37  253.53   36.59  254.06   50.38   254.6   57.52  254.77
    65.7  254.73   91.38  252.83   95.16  252.61  104.74  252.84  116.91  253.77
  126.68  253.59  131.78  254.47  132.32  254.21  142.17  251.41  146.17   251.9
  156.31  252.78  159.48  252.87   163.2  252.49  170.26  254.59  171.04  254.73
  175.21     255  177.52   255.7  178.54  255.89  190.84  257.24
#Mann= 3 , 0 , 0
       0               0       0    .048       0  190.84               0
Levee=-1,131.78,254.47,0,,,,
Bank Sta=0,190.84
XS Rating Curve= 0 ,0
Exp/Cntr=0.3,0.1

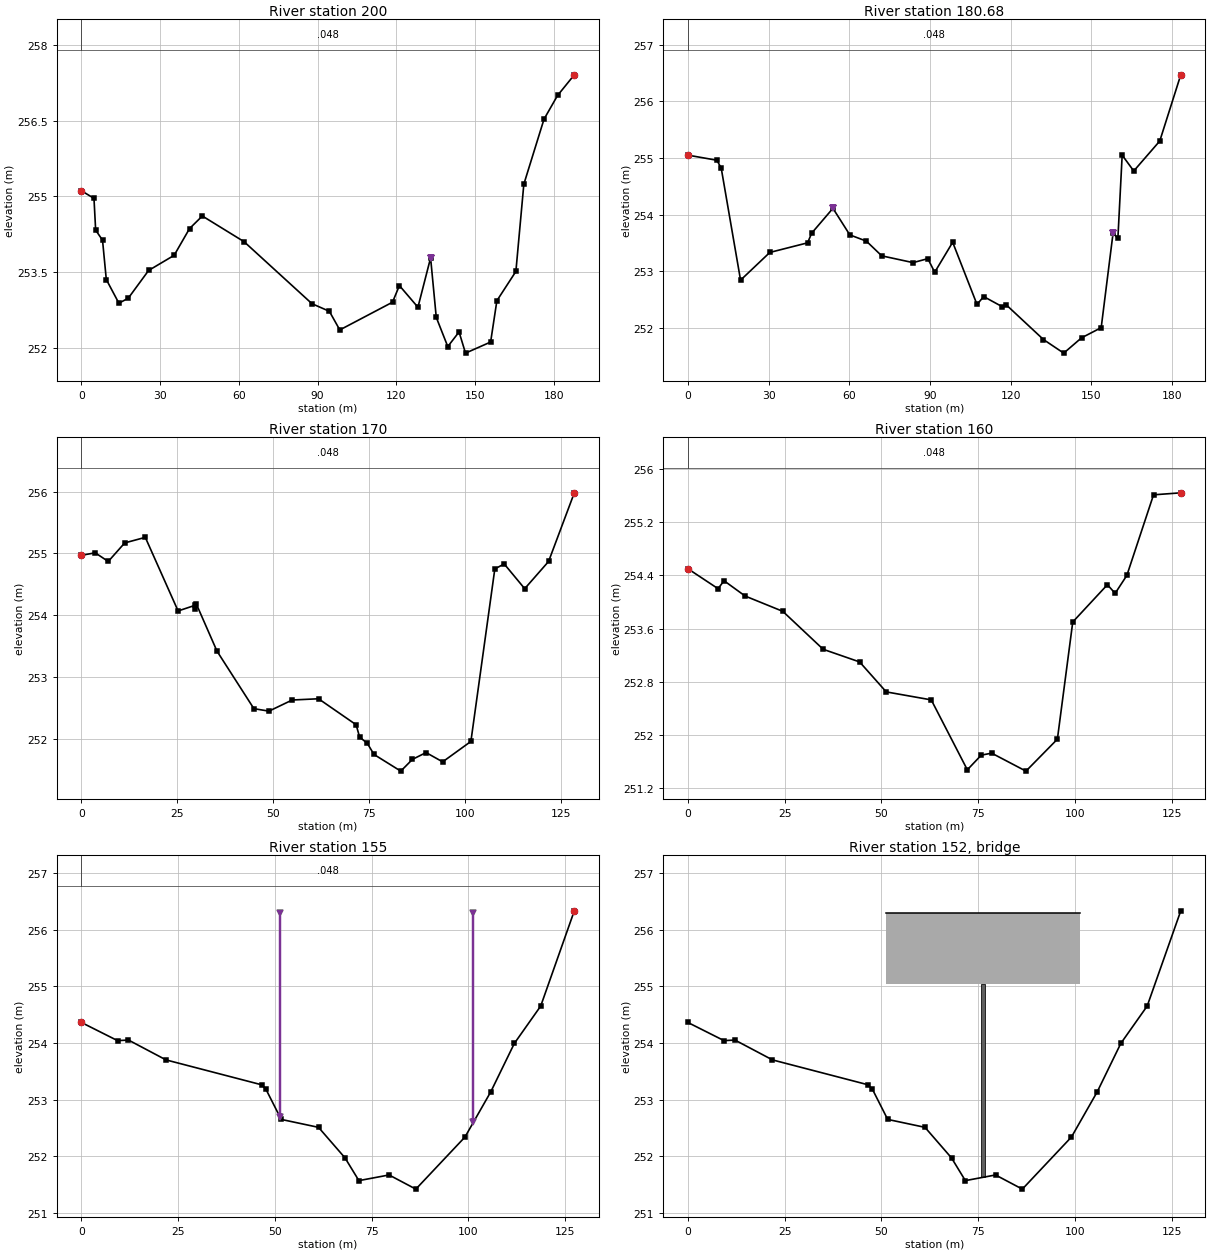
Type RM Length L Ch R = 1 ,200     ,19.32,19.32,19.32
XS GIS Cut Line= 3
925029.5083913821191822.88028758924999.4674034891191957.43842128
924988.2554744551192006.16513518
#Sta/Elev= 30
       0  255.11    4.78  254.96    5.42  254.33    8.04  254.13    9.48  253.35
   14.28  252.88   17.86  252.98   25.61  253.53   35.34  253.83    41.2  254.36
   46.08  254.61      62   254.1   87.88  252.87    94.5  252.72   98.48  252.35
  118.57   252.9   121.2  253.23  128.27   252.8  133.09  253.78  135.25   252.6
  139.64  252.02  143.94  252.31   146.4  251.89  155.97  252.11  158.36  252.93
   165.6  253.51  168.63  255.24  176.32  256.53  181.48     257  187.87  257.41
#Mann= 3 , 0 , 0
       0               0       0    .048       0  187.87               0
Levee=-1,133.09,253.78,0,,,,
Bank Sta=0,187.87
XS Rating Curve= 0 ,0
Exp/Cntr=0.3,0.1

Type RM Length L Ch R = 1 ,180.68  ,10.68,10.68,10.68
XS GIS Cut Line= 3
925048.7942557421191831.83179514925018.2976043721191961.77121656
924997.5387957471192007.02338226
#Sta/Elev= 29
       0  255.05   10.78  254.96   12.39  254.82   19.58  252.84   30.46  253.33
   44.51   253.5   46.01  253.67   53.93  254.11   60.21  253.64   66.36  253.53
   72.07  253.27   83.72  253.15   89.21  253.22   91.77  252.98   98.45  253.51
   107.5  252.41  109.97  252.55  116.92  252.37  118.45   252.4  132.21  251.79
  139.74  251.55  146.35  251.82  153.67     252  158.08  253.67  159.88  253.58
  161.47  255.05  165.78  254.77  175.45   255.3  183.26  256.47
#Mann= 3 , 0 , 0
       0               0       0    .048       0  183.26               0
Levee=-1,53.93,254.11,-1,158.08,253.67,,
Bank Sta=0,183.26
XS Rating Curve= 0 ,0
Exp/Cntr=0.3,0.1

Type RM Length L Ch R = 1 ,170     ,10,10,10
XS GIS Cut Line= 3
925080.4230360451191906.03640409925026.0430773621191968.99426403
925000.3034971751192006.26850778
#Sta/Elev= 28
       0  254.97     3.6  255.01    6.99  254.87   11.28  255.17   16.65  255.26
    25.2  254.07   29.57  254.16   29.58   254.1   29.97  254.18   35.34  253.42
   44.96  252.49   48.89  252.45   54.94  252.63   61.81  252.65   71.61  252.23
   72.52  252.03   74.53  251.93   76.26  251.75   83.25  251.48   86.29  251.67
   89.84  251.78   94.17  251.63  101.53  251.96  107.77  254.75  110.22  254.83
  115.56  254.43  121.78  254.87  128.49  255.98
#Mann= 3 , 0 , 0
       0               0       0    .048       0  128.49               0
Bank Sta=0,128.49
XS Rating Curve= 0 ,0
Exp/Cntr=0.3,0.1

Type RM Length L Ch R = 1 ,160     ,5,5,5
XS GIS Cut Line= 3
925087.6201683621191921.11837676925033.1453183641191976.03402061
924997.9327307651192011.53153772
#Sta/Elev= 20
       0   254.5     7.8   254.2    9.33  254.32   14.78  254.09   24.52  253.86
   34.95  253.29   44.37   253.1   51.25  252.65   62.88  252.53    72.2  251.48
    75.8   251.7   78.49  251.73   87.35  251.46   95.47  251.94   99.44   253.7
  108.39  254.26  110.39  254.13  113.42   254.4  120.31  255.61  127.35  255.64
#Mann= 3 , 0 , 0
       0               0       0    .048       0  127.35               0
Bank Sta=0,127.35
XS Rating Curve= 0 ,0
Exp/Cntr=0.3,0.1

Type RM Length L Ch R = 1 ,155     ,15,15,15
XS GIS Cut Line= 3
925091.1489560331191924.61806475925036.696438865 1191979.5538989
925001.4976559511192015.06510391
#Sta/Elev= 17
       0  254.36    9.33  254.04   12.16  254.05   21.85   253.7    46.6  253.26
   47.69  253.18   51.62  252.65   61.26  252.51   68.12  251.97   71.69  251.57
   79.49  251.67   86.41  251.42   99.11  252.34  105.79  253.14  111.85  253.99
  118.67  254.65  127.35  256.33
#Mann= 3 , 0 , 0
       0               0       0    .048       0  127.35               0
Levee=-1,51.28,256.29,-1,101.28,256.29,,
Bank Sta=0,127.35
XS Rating Curve= 0 ,0
Exp/Cntr=0.5,0.2

Type RM Length L Ch R = 3 ,152     ,,,
Bridge Culvert--1,0,-1,-1, 0
Deck Dist Width WeirC Skew NumUp NumDn MinLoCord MaxHiCord MaxSubmerge Is_Ogee
1,4,1.4,0, 2, 2, , , 0.98, 0, 0,0,,
   51.28  101.28
  256.29  256.29
  255.04  255.04
   51.28  101.28
  256.29  256.29
  255.04  255.04
Pier Skew, UpSta & Num, DnSta & Num=  ,76.28, 2 ,76.28, 2 , 0 , 0 , 0 ,,
     1.2     1.2
     250  255.04
     1.2     1.2
     250  255.04
Abutment Skew #Up #Dn= , 2 , 2
   51.28   51.68
  255.04     250
   51.28   51.68
  255.04     250
Abutment Skew #Up #Dn= , 2 , 2
  100.88  101.25
     250  255.04
  100.88  101.28
     250  255.04
BR Coef=-1 , 0 , 0 ,, 0 ,,,0.8,0,,0,
WSPro=,,,, 1 ,,,, 0 ,,,, 0 ,,,,-1 ,-1 ,-1 , 0 , 0 , 0 , 0 , 0
BC Design=,, 0 ,, 0 ,,,,,,
BC Use User HTab Curves=0
BC User HTab FreeFlow(D)= 0

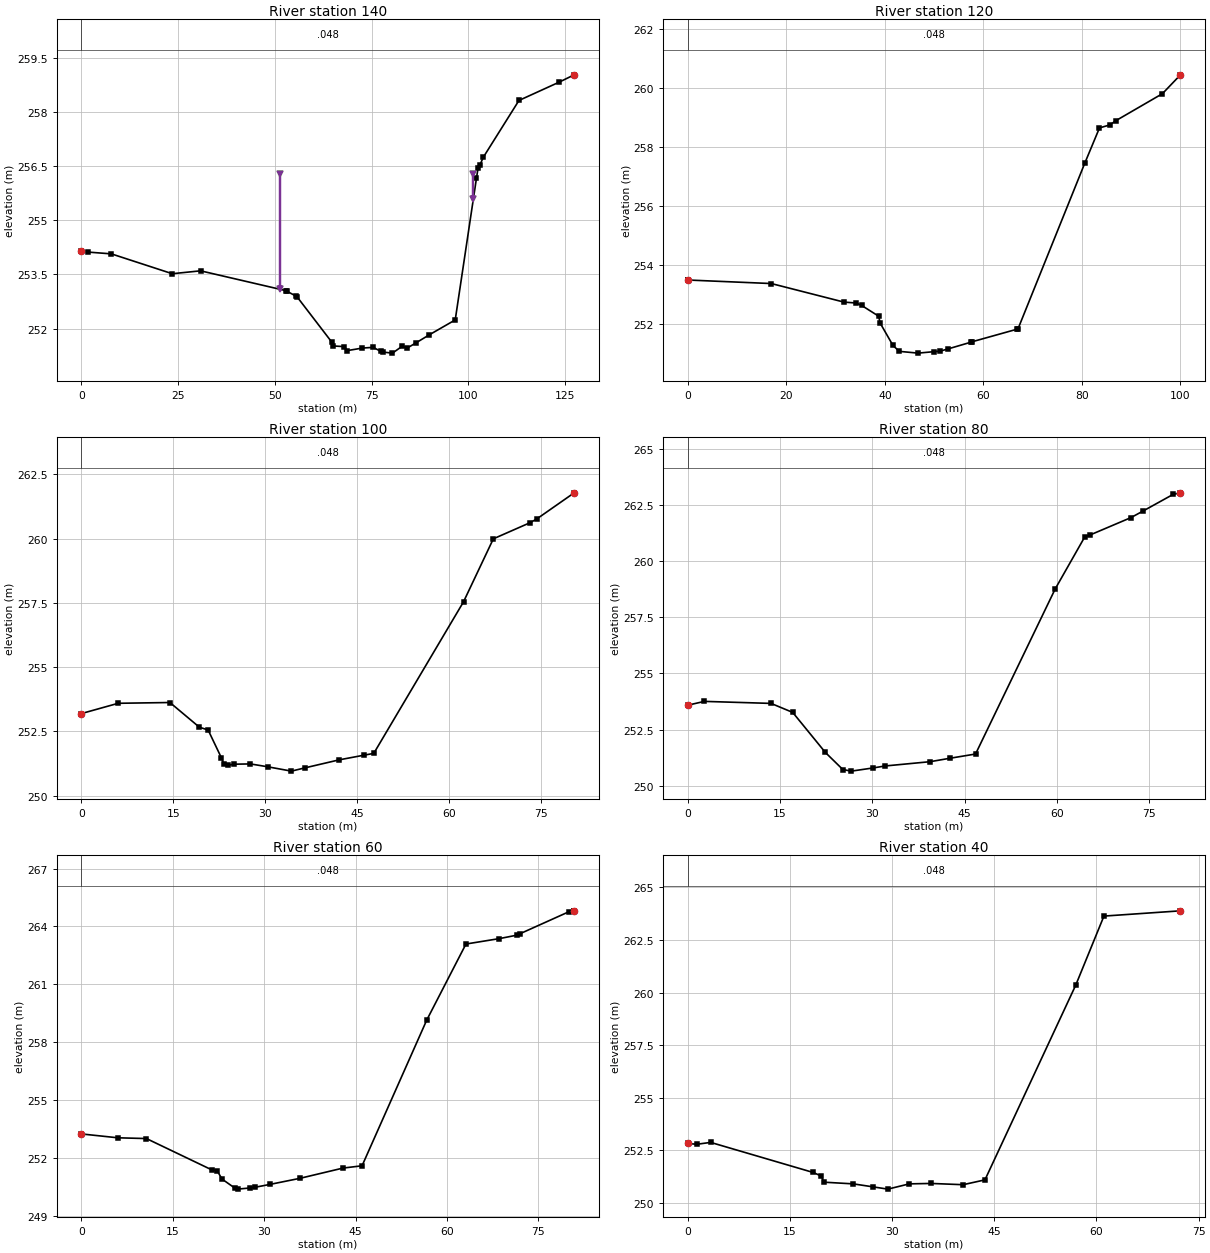
Type RM Length L Ch R = 1 ,140     ,20,20,20
XS GIS Cut Line= 3
925101.827356367 1191935.2048136925047.3476806511191990.11567177
 925012.139918771192025.61797456
#Sta/Elev= 30
       0  254.16    1.62  254.12    7.73  254.07   23.48  253.52    30.8   253.6
   52.88  253.05   53.01  253.04   55.45   252.9    55.8  252.87   64.67  251.63
   64.92  251.52   67.98   251.5   68.72  251.39   72.59  251.46   75.41  251.48
   77.35  251.37   77.83  251.35   80.39  251.32   82.89  251.51   84.19  251.46
    86.4   251.6   89.95  251.83   96.61  252.24  102.09  256.16   102.5  256.44
  102.95  256.52  103.83  256.74  113.08  258.32  123.53  258.83  127.35  259.03
#Mann= 3 , 0 , 0
       0               0       0    .048       0  127.35               0
Levee=-1,51.28,256.29,-1,101.28,256.29,,
Bank Sta=0,127.35
XS Rating Curve= 0 ,0
Exp/Cntr=0.5,0.2

Type RM Length L Ch R = 1 ,120     ,20,20,20
XS GIS Cut Line= 3
925096.7563636481191968.69647373925061.5486017671192004.19877652
925026.3408398861192039.70107931
#Sta/Elev= 24
       0   253.5     .04   253.5   16.96  253.38   31.72  252.75   34.21  252.72
   35.27  252.64   38.77  252.27   39.01  252.05   41.65  251.28   42.94  251.08
   46.74  251.02      50  251.07   51.29  251.09   52.77  251.16   57.45  251.39
   57.59   251.4   66.79  251.83   67.02  251.84   80.57  257.46   83.56  258.66
   85.66  258.76   86.94  258.91   96.33  259.82     100  260.46
#Mann= 3 , 0 , 0
       0               0       0    .048       0     100               0
Bank Sta=0,100
XS Rating Curve= 0 ,0
Exp/Cntr=0.3,0.1

Type RM Length L Ch R = 1 ,100     ,20,20,20
XS GIS Cut Line= 3
 925097.26096858 1191996.8734979925075.7495228821192018.28188127
925040.5417610011192053.78418406
#Sta/Elev= 21
       0  253.19       6  253.59   14.43  253.62   19.23  252.66   20.66  252.55
   22.82  251.47   23.24  251.22   23.91  251.18   24.89  251.22   27.57  251.23
   30.35  251.12   34.24  250.95    36.5  251.08   42.05  251.39   46.06  251.57
   47.67  251.64   62.31  257.54   67.17  259.99   73.18  260.62   74.23  260.76
   80.35  261.78
#Mann= 3 , 0 , 0
       0               0       0    .048       0   80.35               0
Bank Sta=0,80.35
XS Rating Curve= 0 ,0
Exp/Cntr=0.3,0.1

Type RM Length L Ch R = 1 ,80      ,20,20,20
XS GIS Cut Line= 3
925112.5723512411192016.20976178 925088.208437391192033.86299347
925047.8336006441192063.35659545
#Sta/Elev= 19
       0  253.59    2.71  253.76   13.54  253.67   17.06  253.27   22.37  251.49
   25.21  250.73   26.59  250.66   30.09   250.8   32.11  250.89   39.41  251.08
   42.57  251.23   46.78  251.42   59.73  258.76   64.55  261.08   65.42  261.16
   72.05  261.93      74  262.22   78.89  262.96   80.09  263.03
#Mann= 3 , 0 , 0
       0               0       0    .048       0   80.09               0
Bank Sta=0,80.09
XS Rating Curve= 0 ,0
Exp/Cntr=0.3,0.1

Type RM Length L Ch R = 1 ,60      ,20,20,20
XS GIS Cut Line= 3
925125.0027989911192031.90687145925100.0058781821192050.01292817
925059.6310414361192079.50653015
#Sta/Elev= 22
       0  253.25    5.96  253.05   10.67  253.01   21.45  251.38   22.26  251.35
   23.08  250.91   25.15  250.45   25.66  250.39   27.63  250.45   28.56  250.49
   30.87  250.63   35.87  250.95   42.92  251.48   46.06   251.6   56.66  259.14
   63.11  263.09   68.58  263.37   71.49  263.55   72.03  263.63   79.99  264.76
   80.83   264.8   80.87  264.81
#Mann= 3 , 0 , 0
       0               0       0    .048       0   80.87               0
Bank Sta=0,80.87
XS Rating Curve= 0 ,0
Exp/Cntr=0.3,0.1

Type RM Length L Ch R = 1 ,40      ,20,20,20
XS GIS Cut Line= 3
925133.6824157021192050.06615576925111.8033189741192066.16286287
925075.2921822661192092.78050661
#Sta/Elev= 16
       0  252.83    1.32  252.79    3.36  252.88   18.43  251.45   19.62  251.28
   19.98  250.99    24.3  250.91   27.16  250.77   29.38  250.66   32.53  250.91
   35.74  250.93   40.43  250.87   43.64   251.1   56.97  260.35   61.11  263.63
   72.35  263.88
#Mann= 3 , 0 , 0
       0               0       0    .048       0   72.35               0
Bank Sta=0,72.35
XS Rating Curve= 0 ,0
Exp/Cntr=0.3,0.1

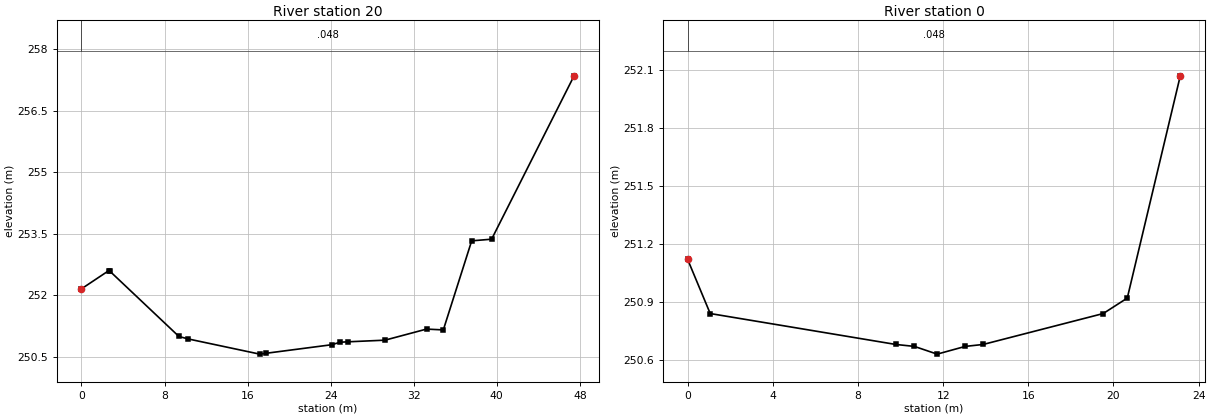
Type RM Length L Ch R = 1 ,20      ,20,20,20
XS GIS Cut Line= 3
925137.9481944971192071.83759157925123.6007597651192082.31279757
925099.6595473651192099.84457918
#Sta/Elev= 16
       0  252.16    2.61   252.6    2.74  252.59    9.39     251   10.28  250.94
   17.17  250.57   17.76  250.59   24.13   250.8    24.9  250.86   25.66  250.87
   29.23  250.91   33.23  251.18   34.85  251.16   37.58  253.33    39.5  253.37
   47.44  257.35
#Mann= 3 , 0 , 0
       0               0       0    .048       0   47.44               0
Bank Sta=0,47.44
XS Rating Curve= 0 ,0
Exp/Cntr=0.3,0.1

Type RM Length L Ch R = 1 ,0       ,,,
XS GIS Cut Line= 3
925140.8227762791192097.09229788925131.6375499881192100.46182596
925119.0701911091192104.99285297
#Sta/Elev= 10
       0  251.12    1.06  250.84    9.78  250.68   10.65  250.67   11.72  250.63
   13.04  250.67   13.88  250.68   19.52  250.84   20.65  250.92   23.14  252.07
#Mann= 3 , 0 , 0
       0               0       0    .048       0   23.14               0
Bank Sta=0,23.14
XS Rating Curve= 0 ,0
Exp/Cntr=0.3,0.1
LCMann Table=0

Chan Stop Cuts=-1
Use User Specified Reach Order=0
Composite Channel Slope=5